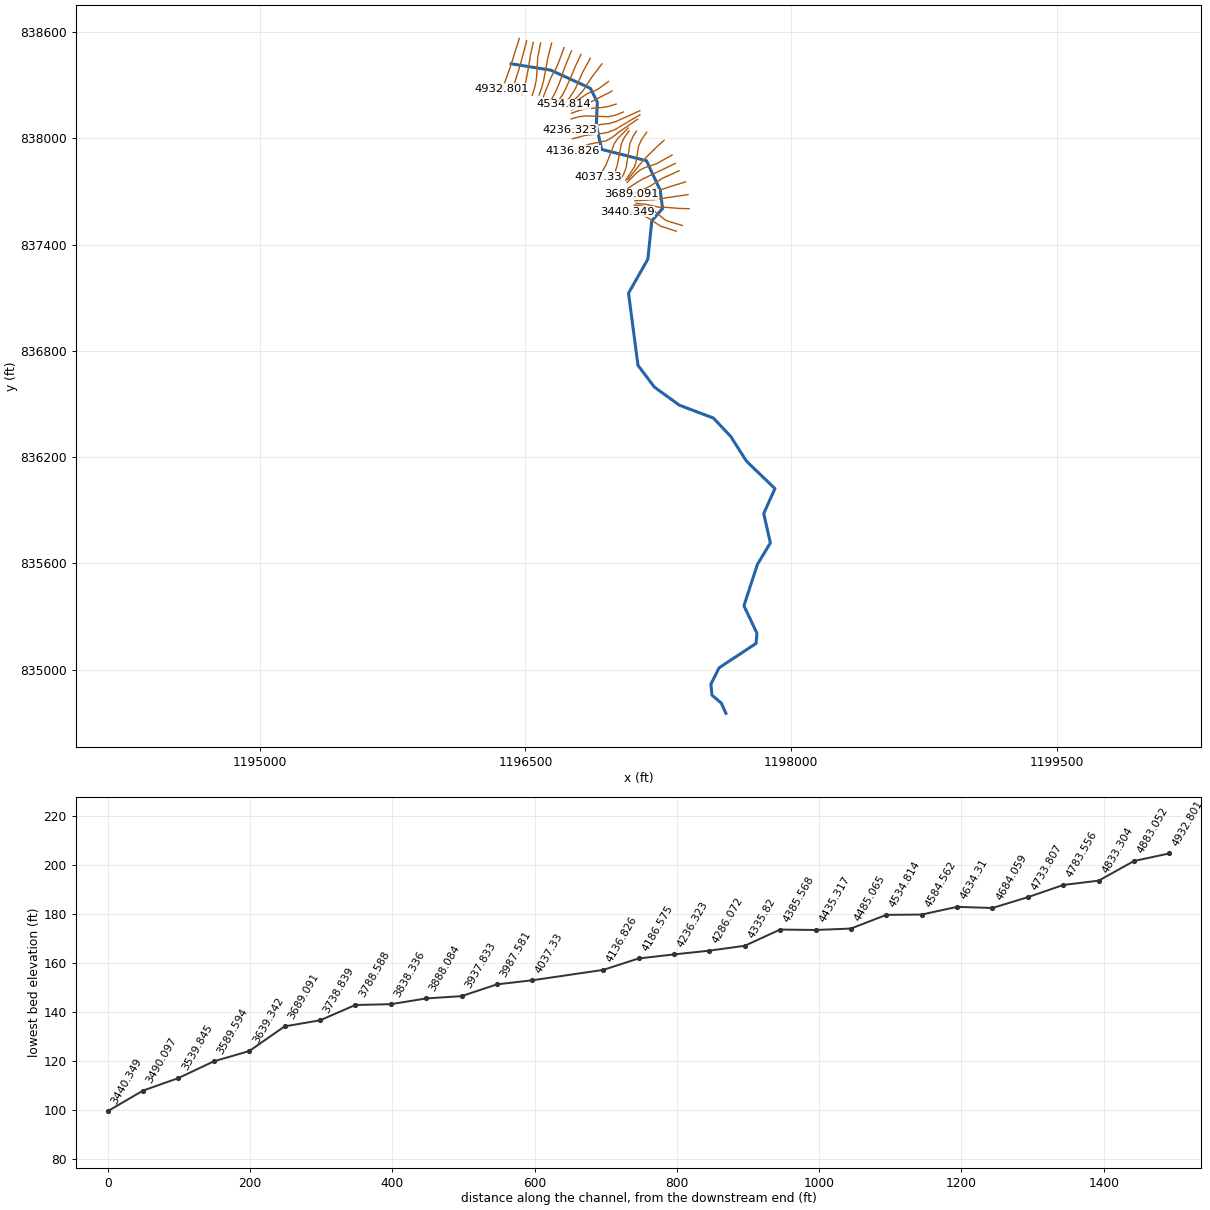
--- 166_ras.prj (project) ---

Proj Title=166
Current Plan=p01
Default Exp/Contr=0.3,0.1
English Units
Geom File=g01
Flow File=f01
Plan File=p01
Y Axis Title=Elevation
X Axis Title(PF)=Main Channel Distance
X Axis Title(XS)=Station
BEGIN DESCRIPTION:
RFD model 166 exported to HEC-RAS
END DESCRIPTION:

--- 166_ras.p01 (plan) ---

Plan Title=Plan 01
Program Version=4.10
Short Identifier=Plan 01
Geom File=g01
Flow File=f01
Subcritical Flow
Calc Critical at every XS
Secant Critical Depth

--- 166_ras.f01 (steady flow) ---

Flow Title=Flow 01
Program Version=4.10
Number of Profiles= 5
Profile Names=10yr,25yr,50yr,100yr,500yr
River Rch & RM=166,39,4932.801
  226.53  408.29  588.23  808.41 1487.22
River Rch & RM=166,39,4485.065
  260.69   471.3  681.01  938.91 1742.08
River Rch & RM=166,39, 4335.82
  266.17  481.42  695.94  959.94 1783.35
River Rch & RM=166,39,4236.323
  270.42  489.29  707.55  976.31 1815.51
River Rch & RM=166,39, 4037.33
  277.11  501.66   725.8 1002.05 1866.14
River Rch & RM=166,39,3987.581
  281.36  509.52  737.42 1018.44 1898.43
River Rch & RM=166,39,3888.084
  283.18   512.9   742.4 1025.47 1912.28
River Rch & RM=166,39,3689.091
  288.04  521.89  755.69 1044.22 1949.25
River Rch & RM=166,39,3589.594
  330.43   600.5  872.03 1208.74 2275.27
River Rch & RM=166,39,3440.349
  332.85  604.99  878.69 1218.17 2294.03
River Rch & RM=166,39,3340.852
  334.06  607.24  882.02 1222.88 2303.41
Boundary for River Rch & Prof#=166,39,1
Up Type= 0
Dn Type= 2
Boundary for River Rch & Prof#=166,39,2
Up Type= 0
Dn Type= 2
Boundary for River Rch & Prof#=166,39,2
Up Type= 0
Dn Type= 2
Boundary for River Rch & Prof#=166,39,2
Up Type= 0
Dn Type= 2
Boundary for River Rch & Prof#=166,39,2
Up Type= 0
Dn Type= 2

--- 166_ras.g01 (geometry) ---

Geom Title=166
Program Version=4.10

River Reach=166,39
Reach XY= 30
1196419.46139902838420.4195591861196642.79466573 838384.58622995
1196866.96126359838282.0862537311196906.12791648838203.752942416
1196900.29458112838074.5863140651196930.29456832837937.086353815
 1197183.6278254837872.919698772 1197261.1277978837706.253079099
1197274.46112425837603.7531090131197213.62780674837533.753131455
1197191.38460672837317.6164546861197082.21796653837125.116514713
1197135.55127238836717.6166335591197228.88457473836594.283333988
1197369.71786375836492.6166932821197561.38447204836420.116709147
 1197658.8844404836316.7834035021197748.05107682836176.783442298
1197908.88435843836021.7834834171197845.55103961835880.950193539
1197883.05102378835715.1169081061197809.71770846835593.450279523
1197733.88439062835360.1170173181197807.21769793835205.117061002
1197802.38629938835147.7331008981197593.05108848835009.283791727
1197547.21776595834917.6171534811197553.05109577834855.950504857
 1197606.3844121834810.117183531 1197632.2177362834752.617199769

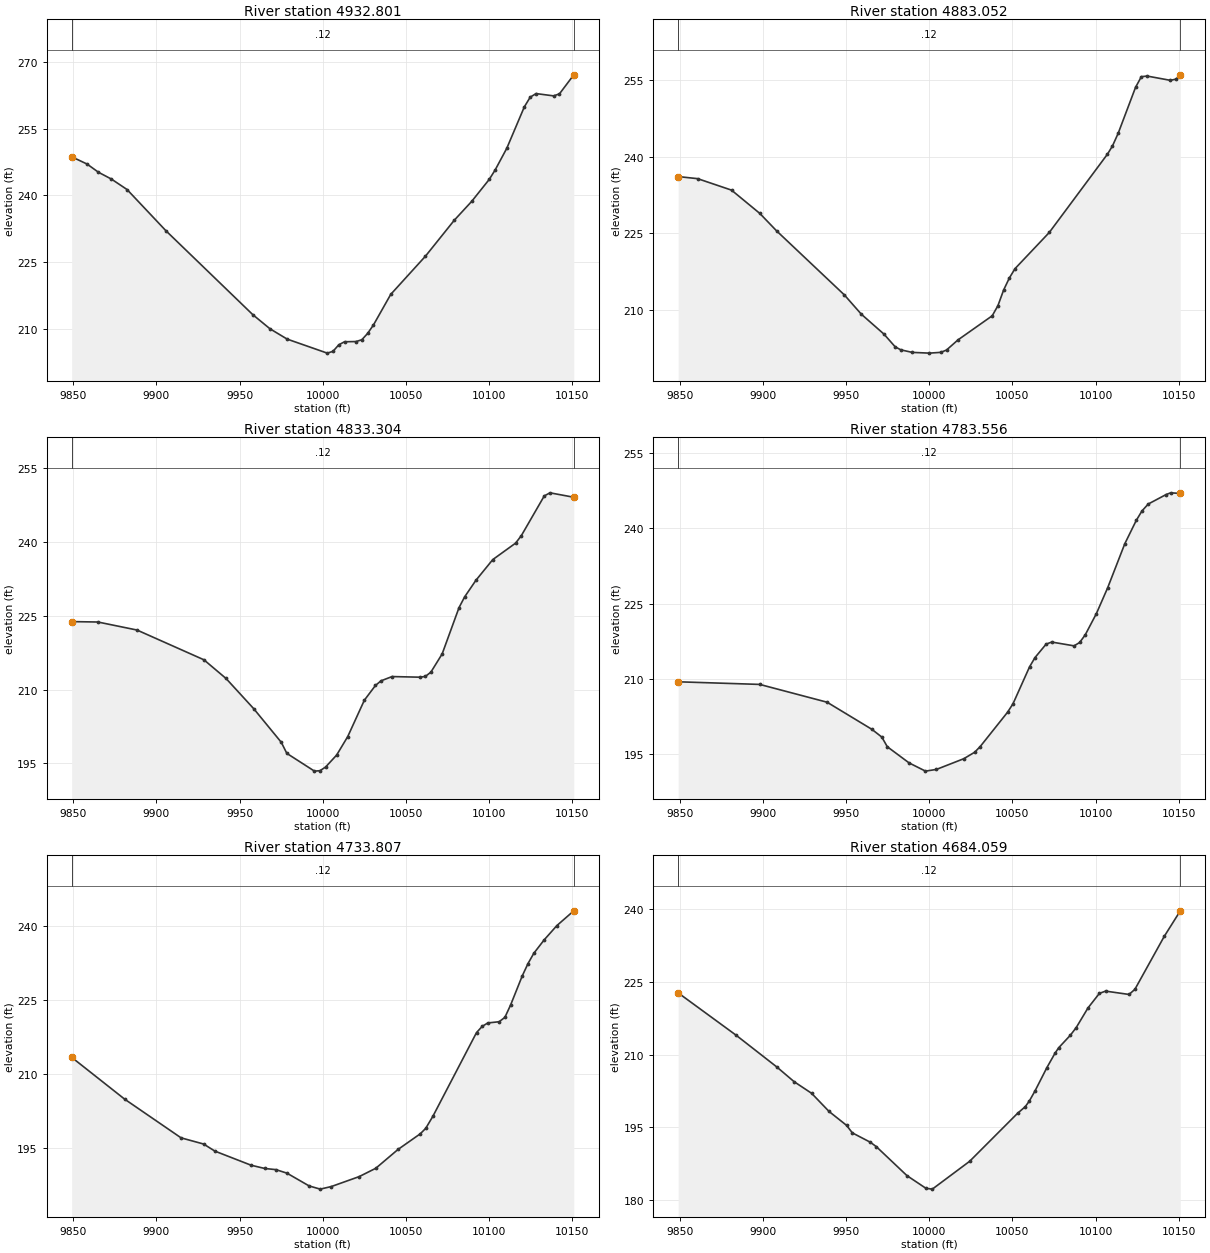
Type RM Length L Ch R = 1 ,4932.801,49.748400,49.748400,49.748400
XS GIS Cut Line= 6
1196465.68935539  838564.1498121 1196420.7263101838421.052014681
1196420.09385451838419.1546481041196415.56253491838405.692529283
1196391.50022684838337.1256723721196368.70652182838278.261620632
#Sta/Elev= 30
9849.004 248.6989858.256247.06629865.134245.21479872.908243.68779882.328241.3326
9905.743232.05149957.986213.18969968.303210.0234 9978.62207.707110002.72204.5552
10006.18204.955810009.64 206.421 10013.1207.108810020.04207.159310023.52207.5632
   10027208.982610030.48210.865410040.91217.763710061.77226.342710079.15234.4431
10089.61238.674210100.16243.617810103.68245.714310110.71250.615910121.27259.9319
10124.79262.097510128.31262.903710138.86262.388210142.38262.842810150.99267.1199
#Mann= 3 , 0 , 0
9849.004    0.12       09849.004    0.12       010150.99    0.12       0
#XS Ineff= 2 , 0
       0                               0
Bank Sta=9849.004,10150.99
Exp/Cntr=0.3,0.1

Type RM Length L Ch R = 1 ,4883.052,49.748400,49.748400,49.748400
XS GIS Cut Line= 6
1196506.96092639838550.2564969121196472.60952847838420.353351166
 1196467.9516401838405.4394347531196467.33599948838403.536545733
1196439.09717118838312.2475168821196420.91513665838260.939969664
#Sta/Elev= 30
9849.007236.09579860.733235.68549881.095233.43649898.063228.88119908.244225.4299
9948.967212.87989959.148209.10359972.722 205.212 9979.51202.70619982.903202.1119
9989.771201.614110000.09201.467410006.96201.619910010.39202.074710017.26204.0563
10037.87208.7907 10041.3210.769910044.73213.841210048.17216.2001 10051.6218.0429
10072.21225.140810107.15240.478810110.17242.082510113.65244.600810124.09253.6119
10127.57255.690410131.05255.808710144.97254.973610148.46255.205110150.99256.0517
#Mann= 3 , 0 , 0
9849.007    0.12       09849.007    0.12       010150.99    0.12       0
#XS Ineff= 2 , 0
       0                               0
Bank Sta=9849.007,10150.99
Exp/Cntr=0.3,0.1

Type RM Length L Ch R = 1 ,4833.304,49.748400,49.748400,49.748400
XS GIS Cut Line= 6
1196544.22923032838541.2052120731196528.79466245 838471.35715472
1196516.15829306838393.9333170741196503.96680233838327.787201499
1196494.27340729838289.1435258371196480.39936815838246.467711645
#Sta/Elev= 30
9849.019223.81569864.799223.73219888.319222.10289928.553216.0617 9941.85212.2695
9958.471 206.1449975.092199.30069978.416197.05619995.037193.45079998.362193.5385
 10001.7194.273910008.37196.710410015.04 200.46110025.05207.857410031.72210.8495
10035.06 211.78910041.73212.655410058.41212.526910061.75212.682310065.08213.5654
10071.83217.255310081.98226.662710085.36228.843810092.12232.199610102.27236.4086
   10116239.753210119.45241.277410133.24 249.34110136.69249.966610150.98249.0693
#Mann= 3 , 0 , 0
9849.019    0.12       09849.019    0.12       010150.98    0.12       0
#XS Ineff= 2 , 0
       0                               0
Bank Sta=9849.019,10150.98
Exp/Cntr=0.3,0.1

Type RM Length L Ch R = 1 ,4783.556,49.748500,49.748500,49.748500
XS GIS Cut Line= 6
1196585.69997896838538.2272360981196569.24412559838454.053807471
1196563.97774387838354.5649061291196560.16193428838323.030786355
1196551.62707601838284.1236525521196537.94220612838241.392894729
#Sta/Elev= 30
9849.023  209.459898.041208.92999938.564205.39099965.521199.99639971.476198.4568
9974.759196.54299987.888193.32019997.735191.6914 10004.3192.030210020.72194.1547
10027.29195.445510030.58196.557610047.08203.401410050.38 205.103 10060.3212.4207
 10063.6214.274210070.27216.939310073.63217.349910087.07216.596210090.43217.2639
10093.79218.7846 10100.5223.016810107.25228.122510117.59236.909310124.48241.5458
10127.92243.422410131.67244.789610142.42246.676510145.15247.016110150.95246.8994
#Mann= 3 , 0 , 0
9849.023    0.12       09849.023    0.12       010150.95    0.12       0
#XS Ineff= 2 , 0
       0                               0
Bank Sta=9849.023,10150.95
Exp/Cntr=0.3,0.1

Type RM Length L Ch R = 1 ,4733.807,49.748400,49.748400,49.748400
XS GIS Cut Line= 6
1196648.10884569838536.9787814771196626.48733647838453.870146164
 1196615.0676956 838390.802463971196602.62644949838324.714651598
1196592.14750559 838286.276602671196577.34337041838243.915845335
#Sta/Elev= 30
9849.032213.43749880.926204.95139914.827197.11389928.387195.86019935.163194.4252
9956.918 191.569 9965.17190.90359971.839190.67399978.507189.95589991.844187.3649
9998.512  186.7210005.19 187.24610021.88189.2525 10031.9190.943810045.25194.7556
 10058.6197.918810061.94199.044110066.25201.491110092.47218.446210095.87219.7057
10099.27 220.40510106.07220.650310109.54221.537310113.02224.081710119.97 229.938
10123.45232.448910126.92234.523310133.22237.268910140.82240.148310150.96243.1313
#Mann= 3 , 0 , 0
9849.032    0.12       09849.032    0.12       010150.96    0.12       0
#XS Ineff= 2 , 0
       0                               0
Bank Sta=9849.032,10150.96
Exp/Cntr=0.3,0.1

Type RM Length L Ch R = 1 ,4684.059,49.748400,49.748400,49.748400
XS GIS Cut Line= 6
1196718.69866816838512.3223541021196681.49373144838413.032351842
 1196670.9402738838390.3163163171196660.30309599838372.326145688
1196644.23854687 838342.976443591196601.37574605  838234.6725596
#Sta/Elev= 30
 9849.02222.69479883.681214.02729908.206207.48149918.717204.42389929.228202.0351
9939.739198.29189950.249195.43679953.753193.88379964.564191.95519968.181191.0451
9986.588185.0837    9998182.475610001.83182.307510024.27188.033810053.08197.9107
10057.69199.269610060.13200.419410063.66202.570110070.72207.317110075.52210.2268
10077.77211.385210084.83213.979410088.36215.560210095.42219.592910102.27222.5848
   10106223.058710120.12222.371910123.64223.428910141.29234.329710150.94 239.581
#Mann= 3 , 0 , 0
 9849.02    0.12       0 9849.02    0.12       010150.94    0.12       0
#XS Ineff= 2 , 0
       0                               0
Bank Sta=9849.02,10150.94
Exp/Cntr=0.3,0.1

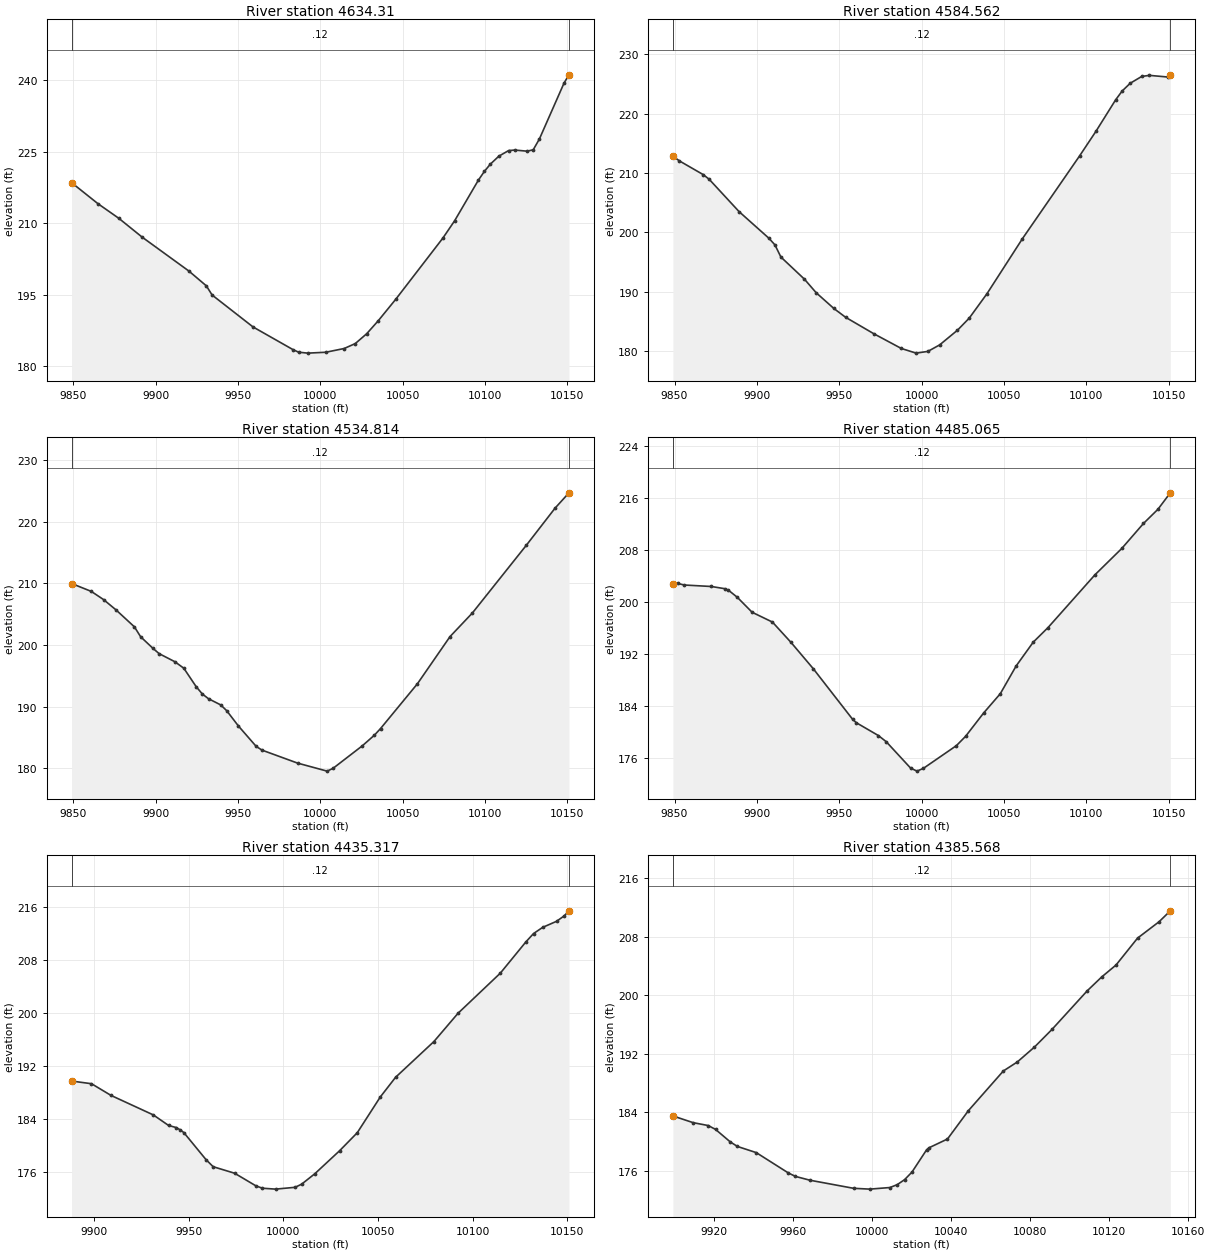
Type RM Length L Ch R = 1 , 4634.31,49.748400,49.748400,49.748400
XS GIS Cut Line= 6
1196759.80329211838493.376023125 1196717.3109345838388.322353228
1196698.56022341838329.7219773311196687.50904613838300.694687728
1196666.32211522838254.1238349541196644.75290459838214.773567137
#Sta/Elev= 30
 9849.02218.54959865.033214.1356 9877.75211.05469891.906207.10599920.219200.0049
9930.836196.89429934.375194.95939959.148188.27549983.409 183.5149986.864182.9668
9992.468182.770810003.35182.954210014.52183.741710021.25184.774210028.21186.8461
10035.23189.577110045.77194.050210074.36206.878710081.56 210.54210095.98219.0705
10099.59 220.88610103.19222.4092 10108.4224.0989 10114.3225.269310118.05225.3859
10125.53 225.14910129.27225.436410133.01227.699910147.98239.440810150.97241.1706
#Mann= 3 , 0 , 0
 9849.02    0.12       0 9849.02    0.12       010150.97    0.12       0
#XS Ineff= 2 , 0
       0                               0
Bank Sta=9849.02,10150.97
Exp/Cntr=0.3,0.1

Type RM Length L Ch R = 1 ,4584.562,49.748400,49.748400,49.748400
XS GIS Cut Line= 6
  1196813.822239838473.5296445751196784.59684852 838411.69435246
1196751.84360176838334.7788749211196725.36792861838275.129759975
1196706.25083083838240.1829007651196681.07809878838203.041568308
#Sta/Elev= 30
9849.007212.84619852.886 212.0339867.402209.7141 9871.03208.92819889.175203.4787
9907.319198.98479910.947197.87399914.576 195.8239928.888192.0861 9936.02189.8008
9946.717187.15879953.848 185.6739970.903182.91369987.656 180.4219996.637 179.634
10003.79 179.92510010.97181.026810021.74 183.49210028.92185.537110039.69189.6538
10061.22198.930910095.89212.865210105.89  217.0410117.77222.313410121.73223.7963
 10126.6225.102310133.62 226.255 10138.3226.431810149.47 226.15310150.96226.5244
#Mann= 3 , 0 , 0
9849.007    0.12       09849.007    0.12       010150.96    0.12       0
#XS Ineff= 2 , 0
       0                               0
Bank Sta=9849.007,10150.96
Exp/Cntr=0.3,0.1

Type RM Length L Ch R = 1 ,4534.814,49.748400,49.748400,49.748400
XS GIS Cut Line= 6
1196866.08821827838450.9664675421196823.22732576838373.181584293
1196787.82022332838292.2797734451196774.73729728838266.661279631
1196751.45664373838232.2016581321196715.49284244838191.368721797
#Sta/Elev= 30
9849.038209.97839860.994208.70199868.486207.36379875.978205.70689887.215202.9338
9890.961201.33679898.453199.44719902.199198.59069911.757197.27629917.183196.2199
9924.675193.22679928.421 192.0379932.167191.26839939.582190.26399943.171189.3359
9950.348186.83159961.113183.52519964.701182.91599986.231180.813610004.14179.5119
 10007.7179.952910025.53183.626210032.88185.357610036.57186.423510058.95 193.695
10078.75  201.3610092.33205.196910124.99216.166310142.47222.208310150.93224.7035
#Mann= 3 , 0 , 0
9849.038    0.12       09849.038    0.12       010150.93    0.12       0
#XS Ineff= 2 , 0
       0                               0
Bank Sta=9849.038,10150.93
Exp/Cntr=0.3,0.1

Type RM Length L Ch R = 1 ,4485.065,49.748400,49.748400,49.748400
XS GIS Cut Line= 6
1196931.61370947838419.7677251761196874.08853206 838343.82486228
 1196832.1787591838278.6342976211196820.38688833838262.825422266
1196788.79121797838228.9507805261196741.61535891838187.026984461
#Sta/Elev= 30
9849.024202.70889851.832202.88189855.948202.62939872.411202.40039880.643202.0565
9882.701201.83879888.135200.73149897.106198.42689909.453196.91299920.736193.7731
9934.148189.7456 9958.11181.91669960.377181.38669973.744  179.419978.487178.4684
9993.287174.39539997.196173.9221 10001.1174.353710021.12177.857210026.68  179.29
10037.65182.894610047.75185.860510057.37190.143310067.75193.818110076.72196.0635
10105.23204.209810121.49208.268310134.65212.121810143.43214.309110150.95216.8486
#Mann= 3 , 0 , 0
9849.024    0.12       09849.024    0.12       010150.95    0.12       0
#XS Ineff= 2 , 0
       0                               0
Bank Sta=9849.024,10150.95
Exp/Cntr=0.3,0.1

Type RM Length L Ch R = 1 ,4435.317,49.748400,49.748400,49.748400
XS GIS Cut Line= 6
1196968.70225739838320.6913385661196916.19348758 838281.68380436
  1196890.129446838266.7837463721196860.03003505838256.666819188
1196842.79667751838248.0536999071196748.47062048838179.713448286
#Sta/Elev= 30
9887.974189.71849898.525189.31219908.855187.53989931.229184.58499939.292182.9879
9943.324182.67429945.475182.31639947.355181.90759959.072177.81659962.851176.7432
9974.188 175.7589985.364173.85959988.851173.48829995.825173.350110006.17173.6256
10009.61174.100310016.59175.680210029.65179.152810039.03181.892410051.18187.2974
10059.28190.285410079.54195.6962 10092.3199.981710114.67206.059910128.16210.7863
10132.21212.051510137.04212.989810144.36213.902710148.42214.729810150.94215.4932
#Mann= 3 , 0 , 0
9887.974    0.12       09887.974    0.12       010150.94    0.12       0
#XS Ineff= 2 , 0
       0                               0
Bank Sta=9887.974,10150.94
Exp/Cntr=0.3,0.1

Type RM Length L Ch R = 1 ,4385.568,49.748400,49.748400,49.748400
XS GIS Cut Line= 6
1196988.90501202 838267.154038761196973.09589169838257.521031416
1196898.78002491838220.4993201511196876.63631173 838208.58100406
1196802.34820094838179.084237681 1196761.7832062838159.899363628
#Sta/Elev= 30
9899.449183.52769909.671182.60729917.355182.20889921.052181.67589928.392179.9906
9932.062179.35499941.603178.51079957.753175.74469961.423175.25639968.763174.7375
9990.783173.6339    9999173.520710009.16173.738910012.89174.134310016.61174.8193
10020.34175.8532 10027.7178.884810028.93179.171110038.29180.373110048.88184.2527
10066.53189.670410073.59190.900610082.27192.939710091.16 195.35910108.97200.6354
10116.23 202.51410123.49 204.14910134.38 207.82610145.27210.067410150.95211.5589
#Mann= 3 , 0 , 0
9899.449    0.12       09899.449    0.12       010150.95    0.12       0
#XS Ineff= 2 , 0
       0                               0
Bank Sta=9899.449,10150.95
Exp/Cntr=0.3,0.1

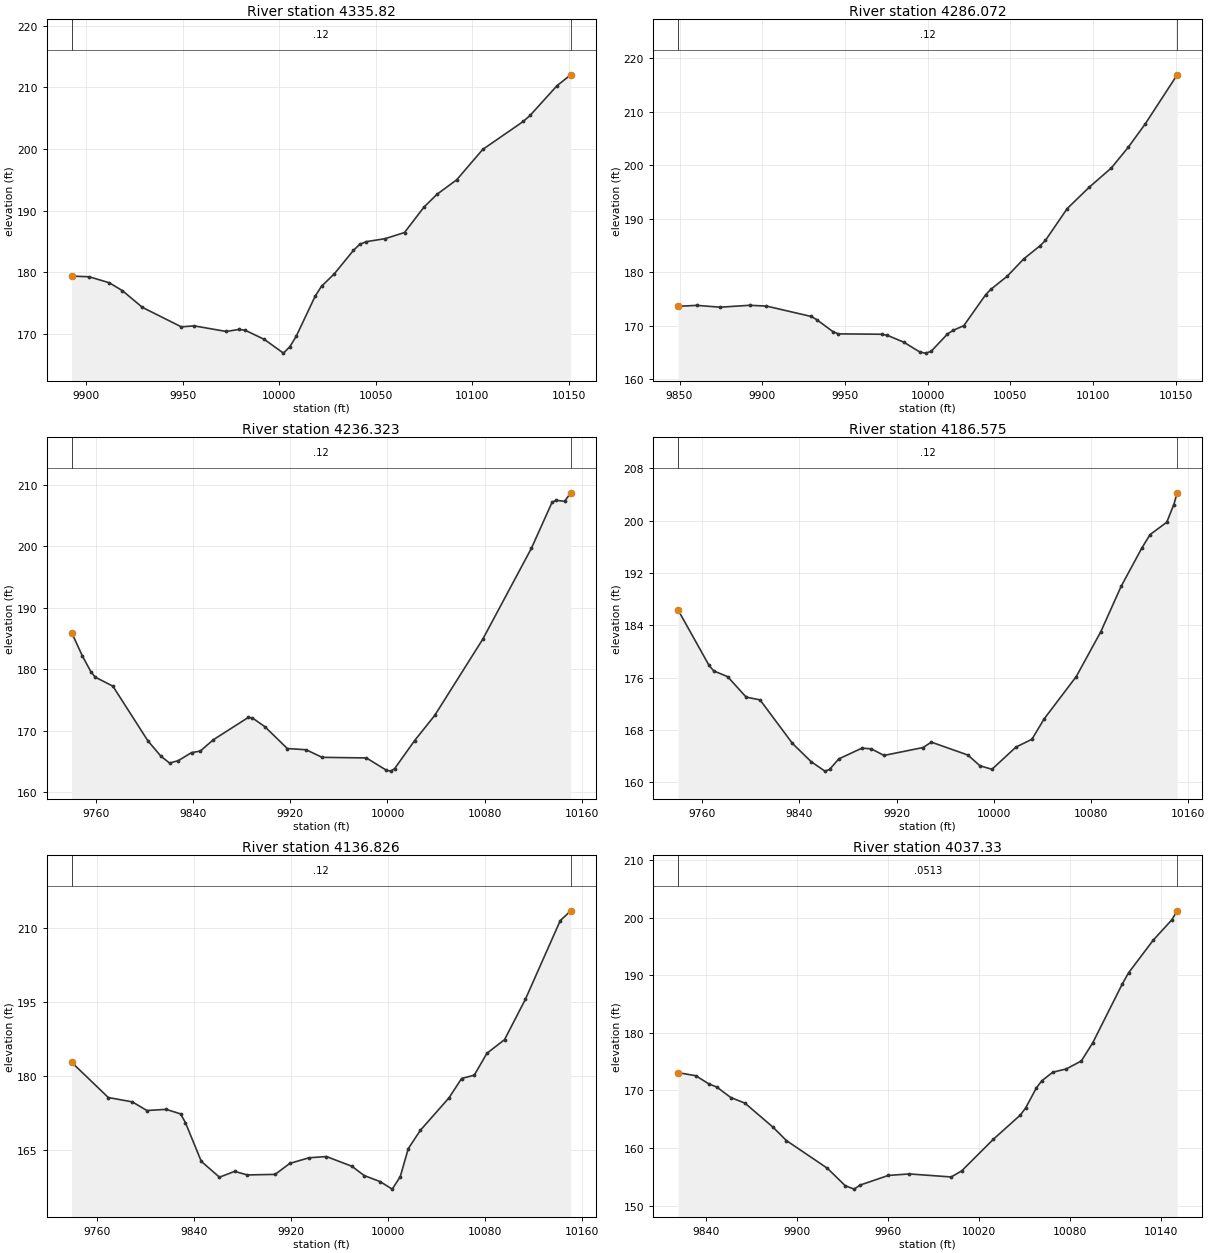
Type RM Length L Ch R = 1 , 4335.82,49.748400,49.748400,49.748400
XS GIS Cut Line= 6
1197011.87473539838192.8466188991196969.95670893838179.868334343
1196935.37227132 838174.084713731196841.04104769838166.063794996
1196802.35500999838156.597078993 1196760.3126809838140.952368213
#Sta/Elev= 30
9892.559179.4011  9901.7179.28579912.004178.32189918.873177.03379929.176174.3314
9949.363171.16819956.016171.32749972.634170.4155 9979.21170.75349982.498170.6122
9992.361169.125910002.22166.9061 10005.5167.937310008.79169.609110018.64176.1381
10021.93177.7538 10028.5179.745710038.41183.550210041.72184.550110045.03184.9778
10054.96185.4727 10064.9186.4656   10075190.597910081.76192.673810091.89195.0044
 10105.4199.937610126.38204.474610129.88205.444410143.88210.281710150.94212.0339
#Mann= 3 , 0 , 0
9892.559    0.12       09892.559    0.12       010150.94    0.12       0
#XS Ineff= 2 , 0
       09901.586                       0
Bank Sta=9892.559,10150.94
Exp/Cntr=0.3,0.1

Type RM Length L Ch R = 1 ,4286.072,49.748400,49.748400,49.748400
XS GIS Cut Line= 6
1197053.00239501838148.2721966941197011.23718511838131.314817388
1196966.83228271838121.4499762551196840.73952645838126.450471599
1196801.27072621838121.2021809031196758.08746849838109.096285976
#Sta/Elev= 30
9849.109173.66659860.431173.84279874.595173.5034  9892.3173.85689902.559173.7126
9929.518171.77379932.845171.20029942.785168.92279946.069168.51869972.343168.4448
9975.635168.24579985.533166.97239995.432165.10239998.731164.918110002.05165.2322
10011.97168.484810015.27169.154410021.88 170.05510035.06175.821110038.34176.8706
10048.18179.305710058.02 182.50310067.88184.955910071.19185.968610084.43191.9453
10097.67195.912410111.05 199.51310121.27203.3746 10131.5207.722310150.89216.9297
#Mann= 3 , 0 , 0
9849.109    0.12       09849.109    0.12       010150.89    0.12       0
#XS Ineff= 2 , 0
       09897.938                       0
Bank Sta=9849.109,10150.89
Exp/Cntr=0.3,0.1

Type RM Length L Ch R = 1 ,4236.323,49.748400,49.748400,49.748400
XS GIS Cut Line= 6
1197145.65577802838154.974243149  1197012.533337838094.838565856
1196972.20418602838083.3432222311196816.79325244838063.518976077
1196778.87551633838055.6654663531196752.21346736838047.808285952
#Sta/Elev= 30
9739.723185.97319748.501182.18849755.701179.54569759.301178.68659773.701177.2392
9802.501168.34419813.302165.81199820.502164.69399827.702165.10139838.502166.4005
9845.702166.64749856.502168.49519885.303172.1358 9888.74172.03979898.975170.6269
9917.439167.06789932.932166.86679946.175165.62939982.594165.5344    9999163.5393
10002.53 163.38310005.86163.785410022.38168.373310038.89172.458310078.51184.8922
10118.62199.721110135.63207.211910139.05207.520610145.89207.356910150.96208.7388
#Mann= 3 , 0 , 0
9739.723    0.12       09739.723    0.12       010150.96    0.12       0
#XS Ineff= 2 , 0
       09889.263                       0
Bank Sta=9739.723,10150.96
Exp/Cntr=0.3,0.1

Type RM Length L Ch R = 1 ,4186.575,49.748400,49.748400,49.748400
XS GIS Cut Line= 6
1197146.49337402838132.359152466 1197005.8768225838049.015246287
1196967.19936171838033.811658099 1196936.7947011838027.565718755
1196838.28118232838016.2452573331196765.28060454837996.746228367
#Sta/Elev= 30
9740.077186.35739765.605 177.8839769.419177.0473 9780.86176.17249796.115173.0451
9807.557172.62199834.253165.96429849.509163.1989 9860.95161.73349864.764161.9833
9872.392163.60479891.461165.24759899.088165.14119909.606164.13339941.727165.3374
9948.594166.16249978.695164.18949988.576162.55649998.456162.013510018.21165.4017
 10031.4166.607910041.35169.692810067.89176.191310087.98182.999910104.82189.9678
10121.73195.778710128.61197.876110142.36199.764910148.17202.454110150.96204.2618
#Mann= 3 , 0 , 0
9740.077    0.12       09740.077    0.12       010150.96    0.12       0
#XS Ineff= 2 , 0
       09921.809                       0
Bank Sta=9740.077,10150.96
Exp/Cntr=0.3,0.1

Type RM Length L Ch R = 1 ,4136.826,99.496800,99.496800,99.496800
XS GIS Cut Line= 6
1197133.09183881838107.2312739491197036.23758572838040.898091972
1196992.61895818 838006.577231751196956.02941129837985.514758199
1196859.97843897837966.3163020161196768.89915159837929.696361959
#Sta/Elev= 30
9739.307182.81899769.563175.66659789.446174.77599801.375173.02569817.281173.2638
9829.211172.33789833.187170.56089846.262162.71039861.238159.4917 9873.69160.6708
9884.302159.9517 9907.16 160.0659919.198162.28239935.061 163.4359949.472163.6849
9970.413161.72019980.621159.82919993.835 158.59410003.74157.071210010.35 159.595
10016.96165.287810026.98169.025510050.56175.599210060.94179.522610071.39180.2042
10081.84184.642610096.36187.406610113.57195.605110142.33211.583210150.95213.5598
#Mann= 3 , 0 , 0
9739.307    0.12       09739.307    0.12       010150.95    0.12       0
#XS Ineff= 2 , 0
       09944.311                       0
Bank Sta=9739.307,10150.95
Exp/Cntr=0.3,0.1

Type RM Length L Ch R = 1 , 4037.33,49.748400,49.748400,49.748400
XS GIS Cut Line= 6
1197080.32329386 838057.813112811197022.26795232838000.038515195
1197002.05253643837970.0188539031196956.68036813837853.057823345
1196937.55180106837818.7691118721196910.08327729837781.453268245
#Sta/Elev= 30
9821.605 173.0879833.292172.54439841.876171.13439847.178170.57479856.435168.7504
9865.692167.79049884.206163.62119893.038161.2937 9920.13156.47339931.877153.4494
9937.751152.8505 9941.87153.56819960.336155.23039974.207155.488310001.83154.9637
10008.73156.018210029.54161.487910047.34 165.695 10050.9 166.92910058.02170.4289
10061.58171.661810068.89173.1636 10077.7173.717610087.67175.106410095.19178.2557
10114.76188.504210118.83 190.41410135.13196.092210147.35 199.60810150.92201.1839
#Mann= 3 , 0 , 0
9821.605  0.0513       09821.605  0.0513       010150.92  0.0513       0
#XS Ineff= 2 , 0
       09947.637                       0
Bank Sta=9821.605,10150.92
Exp/Cntr=0.3,0.1

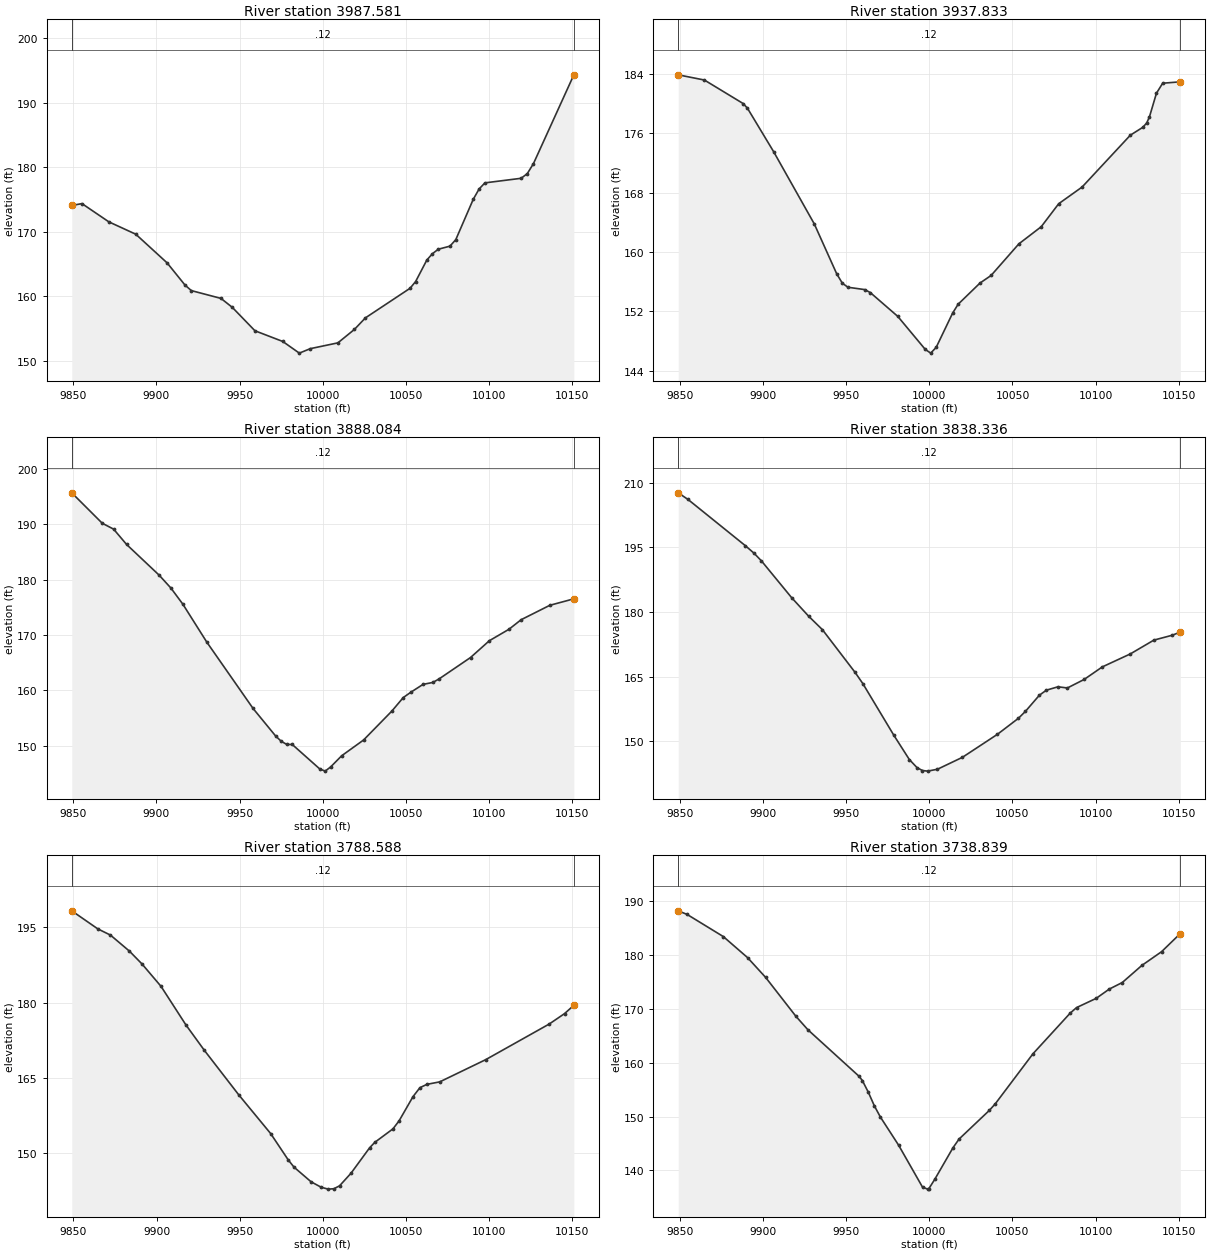
Type RM Length L Ch R = 1 ,3987.581,49.748400,49.748400,49.748400
XS GIS Cut Line= 6
1197085.30290928838041.9217132651197059.09257078838005.535651179
1197041.89632474837969.6588197561197016.83500491837839.785835439
1197002.75501542 837802.551989791196980.01476551837763.923069964
#Sta/Elev= 30
9849.143174.07579855.268174.36569871.441171.53499887.615169.62049906.445165.1773
9917.166161.74789920.998  160.889938.835159.66869945.637158.2789 9959.24154.6515
9975.971152.99219985.914151.18529992.542151.8797 10009.1152.777310019.03154.8615
10025.65156.652510052.46161.236410055.83162.287610062.56165.618510065.92166.5965
10069.41167.290610076.43167.768310079.94168.767410090.46175.035610093.97176.6317
10097.47177.580210119.24178.289110122.95179.018210126.66180.573610150.92194.3297
#Mann= 3 , 0 , 0
9849.143    0.12       09849.143    0.12       010150.92    0.12       0
#XS Ineff= 2 , 0
       0                               0
Bank Sta=9849.143,10150.92
Exp/Cntr=0.3,0.1

Type RM Length L Ch R = 1 ,3937.833,49.748400,49.748400,49.748400
XS GIS Cut Line= 6
1197127.07875613838040.2675003491197107.57132461838010.506352357
1197090.43424632837971.5546157881197068.83502307837834.508741931
1197054.66303006837797.3303172061197031.17621413837759.151496403
#Sta/Elev= 30
9849.082183.88479864.814183.18179888.121180.01249890.689179.38649906.398173.5396
9930.871163.79269944.359157.06479947.731155.80559951.104155.2591 9961.22154.9432
9964.541154.54219981.048151.33539997.554146.890710000.85146.382810004.15147.1606
10014.03151.775810017.33152.968810030.51155.830710037.14156.844610053.86 161.109
10067.28163.414410077.81166.518610091.85168.762110120.88175.7553 10128.4176.8182
10130.72177.404810132.36178.230510136.56181.4082 10140.3182.7538 10150.9182.9417
#Mann= 3 , 0 , 0
9849.082    0.12       09849.082    0.12       0 10150.9    0.12       0
#XS Ineff= 2 , 0
       0                               0
Bank Sta=9849.082,10150.9
Exp/Cntr=0.3,0.1

Type RM Length L Ch R = 1 ,3888.084,49.748400,49.748400,49.748400
XS GIS Cut Line= 6
1197184.81515254838034.1502003941197155.16206835837990.899403326
1197138.31011929837953.6539326141197124.71488838837866.012796933
1197115.64985512837838.6457829281197066.23793146837762.916362553
#Sta/Elev= 30
9849.123195.67629867.425190.18879874.271189.1225 9882.04186.36599901.609180.8213
9908.678178.4968 9915.88175.57919930.284168.72169958.086  156.759971.616  151.79
9974.999150.82949978.327150.26169981.623150.25279998.104145.850710001.39145.4445
10004.69146.199810011.29148.211310024.48151.062810041.43156.266910048.34158.7249
10052.86159.680210060.24161.105210066.11161.451510069.89 162.09610088.76165.9518
10100.08 168.98610111.86171.050810119.16172.774210136.41175.376910150.84176.5432
#Mann= 3 , 0 , 0
9849.123    0.12       09849.123    0.12       010150.84    0.12       0
#XS Ineff= 2 , 0
       0                               0
Bank Sta=9849.123,10150.84
Exp/Cntr=0.3,0.1

Type RM Length L Ch R = 1 ,3838.336,49.748400,49.748400,49.748400
XS GIS Cut Line= 6
1197283.09852501837988.540467345 1197240.9146699837950.530126908
1197174.80622202 837884.842103951197173.28234335837883.546807153
1197166.29232696837876.8287315391197078.46816396837767.455394628
#Sta/Elev= 30
9849.023 207.683  9854.9206.14559889.428 195.4039894.646193.65589899.063191.8881
9917.244183.34289927.489179.03739935.744175.92229955.417165.99669960.071163.3919
 9978.69151.42399987.999 145.7979992.654 143.906 9995.87143.2469    9999143.1031
10004.91143.539310019.93146.307810040.97151.642910053.59155.3602 10057.8156.9633
10066.21160.719310070.42161.888210077.39162.672610083.04162.399310093.11164.3721
10104.08167.295210120.91 170.30310135.03 173.50110146.16174.641110150.96175.3886
#Mann= 3 , 0 , 0
9849.023    0.12       09849.023    0.12       010150.96    0.12       0
#XS Ineff= 2 , 0
       0                               0
Bank Sta=9849.023,10150.96
Exp/Cntr=0.3,0.1

Type RM Length L Ch R = 1 ,3788.588,49.748400,49.748400,49.748400
XS GIS Cut Line= 6
1197328.33164165837905.4195052841197241.30031378837856.740857421
1197172.34748974837832.999776645 1197151.0005411837822.607430101
1197124.02987171 837801.349192161197074.14102528837750.803802816
#Sta/Elev= 30
9849.029198.31219864.686194.7088 9872.29193.46939883.696190.2692  9891.3187.6924
9902.706183.23589917.664175.54479928.764170.46479949.394161.60579968.607153.8679
9979.215148.59529982.641147.17019992.919144.2409    9999143.152710003.18142.7804
10006.61142.856310010.04143.4408 10016.9145.946110028.05151.004510031.18152.1069
10042.13154.803810045.81156.399310054.17161.227210058.34163.021210062.52163.6849
10070.27164.183810097.84168.604910136.06 175.71910145.28 177.79810150.89179.4531
#Mann= 3 , 0 , 0
9849.029    0.12       09849.029    0.12       010150.89    0.12       0
#XS Ineff= 2 , 0
       0                               0
Bank Sta=9849.029,10150.89
Exp/Cntr=0.3,0.1

Type RM Length L Ch R = 1 ,3738.839,49.748500,49.748500,49.748500
XS GIS Cut Line= 6
1197345.90809459837857.2919282591197210.47265065837792.857779952
1197208.66609561837791.9996663731197164.45113071837770.808167921
1197131.69055831837751.8993760531197079.03187928837717.087089878
#Sta/Elev= 30
9849.018188.21989854.378 187.5479876.177183.4256 9890.71179.5276 9901.61175.8398
9919.776168.63139927.042166.1118 9957.76 157.4849959.741156.69579963.374154.4985
9967.008151.96319970.641149.8897 9981.54144.68999995.944136.8826    9999136.5164
9999.706136.576510003.34138.359710014.26144.2019 10017.9145.813510036.09151.1342
10039.72152.376910062.36161.662310084.76169.218110088.57170.240910100.37171.9547
10108.24173.6777 10116.1174.9034 10127.9178.0877 10139.7180.625310150.98183.9983
#Mann= 3 , 0 , 0
9849.018    0.12       09849.018    0.12       010150.98    0.12       0
#XS Ineff= 2 , 0
       0                               0
Bank Sta=9849.018,10150.98
Exp/Cntr=0.3,0.1

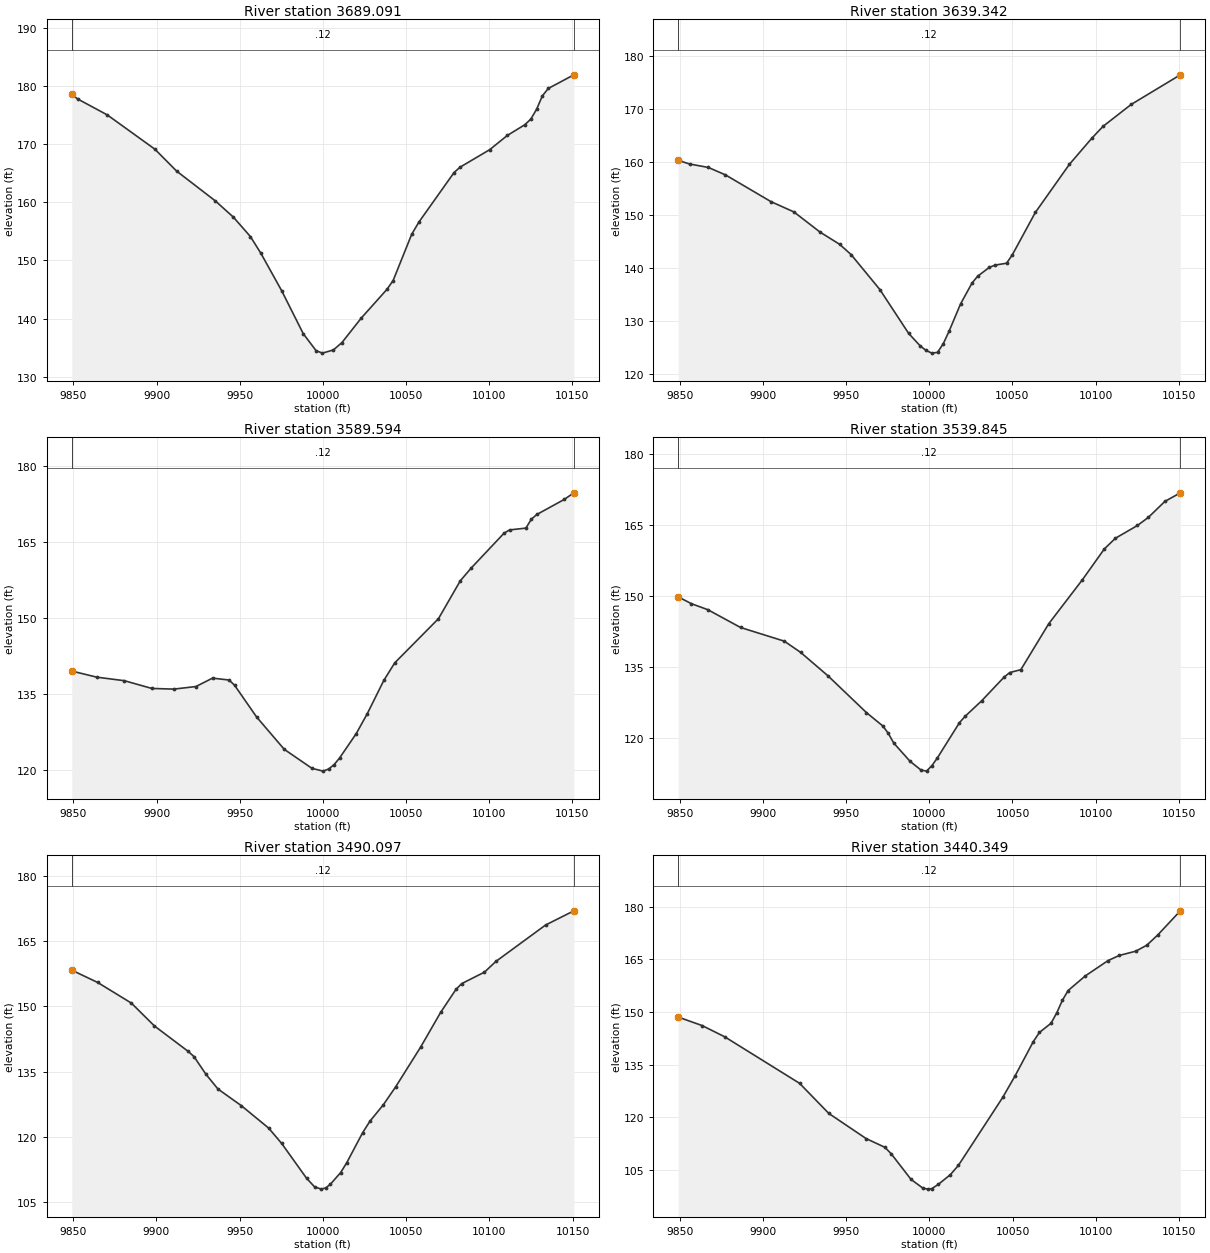
Type RM Length L Ch R = 1 ,3689.091,49.748400,49.748400,49.748400
XS GIS Cut Line= 6
1197367.21763835837816.230813837 1197273.0192157837773.223319077
1197206.23782269  837731.33415831197180.86974372837717.535285564
1197147.81264879837702.7377197421197097.02600818837683.135923958
#Sta/Elev= 30
9849.035178.57319852.508177.78879870.405 175.034 9899.04 169.1349912.118165.3636
9935.319160.25549946.258157.44029956.463 154.1089962.731151.24519975.268144.7889
9988.256137.39789995.957134.48079999.805134.053910006.41134.608510011.52 135.871
10023.25140.124410038.55145.012910042.29146.538810053.49154.515710057.86 156.626
10078.91165.110310082.51166.034310100.39169.059910110.94171.495910121.49173.3429
10125.07174.301610128.53 175.97510132.04 178.30210135.56179.579910150.98 181.931
#Mann= 3 , 0 , 0
9849.035    0.12       09849.035    0.12       010150.98    0.12       0
#XS Ineff= 2 , 0
       0                               0
Bank Sta=9849.035,10150.98
Exp/Cntr=0.3,0.1

Type RM Length L Ch R = 1 ,3639.342,49.748400,49.748400,49.748400
XS GIS Cut Line= 6
1197404.30234382837753.5196799871197319.07843812837727.445654507
1197261.32035181 837708.233030261197259.50222214837707.399720891
1197191.45358628837684.5419621611197115.49921556837666.006133453
#Sta/Elev= 30
9849.007160.38289855.842159.70439867.101159.05039877.394157.64989904.842152.5837
9918.566150.65549934.341146.83269946.074144.53979952.989142.59229970.277135.9928
9987.565127.7272 9994.48125.37349997.938124.527510001.48123.991510004.94124.1335
 10008.4125.763610011.86128.101610018.78133.263510025.71137.235510029.17138.5361
10036.09140.173910039.55140.611910046.47140.965810049.93142.548510063.78150.5529
10084.26159.636410097.77164.575410104.52166.813610121.41170.943410150.97176.5379
#Mann= 3 , 0 , 0
9849.007    0.12       09849.007    0.12       010150.97    0.12       0
#XS Ineff= 2 , 0
       0                               0
Bank Sta=9849.007,10150.97
Exp/Cntr=0.3,0.1

Type RM Length L Ch R = 1 ,3589.594,49.748400,49.748400,49.748400
XS GIS Cut Line= 6
1197418.29068832837681.6043814271197296.72046091837664.149793381
1197269.99584006 837659.229385061197268.05213983837658.758185064
1197238.04125236837653.7175298761197118.71764878837646.853384986
#Sta/Elev= 30
9849.009  139.579864.049138.36679880.621137.66769897.194136.13639910.452 136.009
9923.709136.51919933.653138.17549943.596137.80339946.911136.77139960.169130.5039
9976.773124.12499993.453120.368910000.14119.817710003.48120.2339 10006.8121.1058
10010.13122.440110020.11127.239110026.77131.186410036.68137.729810043.25141.1925
10069.54149.914710082.69 157.40210089.26159.920310108.98166.787910112.26167.4285
10122.12167.789510125.41 169.557 10128.7 170.47810145.13173.436910150.95174.7531
#Mann= 3 , 0 , 0
9849.009    0.12       09849.009    0.12       010150.95    0.12       0
#XS Ineff= 2 , 0
       0                               0
Bank Sta=9849.009,10150.95
Exp/Cntr=0.3,0.1

Type RM Length L Ch R = 1 ,3539.845,49.748400,49.748400,49.748400
XS GIS Cut Line= 6
1197424.45180427 837602.209368051197369.49604026837603.724342963
1197290.07060045837610.0293179931197259.88797931837609.430632597
1197179.19664354 837627.059351921197125.05919269 837632.27165539
#Sta/Elev= 30
9849.031149.80719856.959148.37179866.805147.10359886.498143.34069912.779 140.454
9922.652138.07549939.108133.11099962.146125.36939972.019122.5291 9975.31120.9901
9978.602118.91869988.461115.04189995.025113.20849998.307112.9826 10001.6114.1672
10004.88115.7941 10018.1123.217110021.46124.546510031.54127.872210044.97132.8544
10048.33133.810110055.04134.430110071.83144.146310091.98   153.410105.28159.9641
 10111.9162.200510125.13164.896710131.72166.613510141.58169.974210150.91171.7996
#Mann= 3 , 0 , 0
9849.031    0.12       09849.031    0.12       010150.91    0.12       0
#XS Ineff= 2 , 0
       0                               0
Bank Sta=9849.031,10150.91
Exp/Cntr=0.3,0.1

Type RM Length L Ch R = 1 ,3490.097,49.748400,49.748400,49.748400
XS GIS Cut Line= 6
1197385.78384761837507.4285056151197293.03627858837535.803613892
1197227.22745804 837589.104634531197196.77279118837605.827710722
1197158.70824645837617.4237091591197114.20526347837622.877509186
#Sta/Elev= 30
9849.113158.3727  9864.7155.53149884.901150.78449898.764145.51469919.111139.6344
9922.577138.42889929.737134.36439936.928130.98049950.949127.14369967.373121.9724
9975.191118.44269990.155110.41139994.966108.4226    9999107.887510001.77108.1778
10004.52109.032810010.61111.6781 10014.3  113.9610023.88120.905510028.31123.5777
10036.27127.314910043.75 131.49210058.73140.642410070.72148.628210079.92153.9221
10083.35155.263510097.07157.915210103.93160.385210133.75168.769410150.77 172.053
#Mann= 3 , 0 , 0
9849.113    0.12       09849.113    0.12       010150.77    0.12       0
#XS Ineff= 2 , 0
       0                               0
Bank Sta=9849.113,10150.77
Exp/Cntr=0.3,0.1

Type RM Length L Ch R = 1 ,3440.349,49.748400,49.748400,49.748400
XS GIS Cut Line= 6
1197351.65030979837475.2328446051197263.08009402837503.920376751
 1197190.0229547837551.2863040531197155.29373478837568.651666572
 1197115.8907039837580.5534977571197075.00874321837586.086951732
#Sta/Elev= 30
9849.082148.54899863.424 146.1349877.001 142.9319922.013129.65499939.614121.0534
9961.999113.89539973.285111.39999977.047109.57439988.966102.26329996.11299.74872
    999999.4703710001.4299.5950210005.42100.827410012.59103.579810017.43106.2116
10044.13 125.65710051.46131.721810062.47 141.53310066.13144.157110073.14146.7811
10076.57149.747910079.99153.361410083.42 156.128 10093.7160.286210107.41164.6676
10114.11166.127110124.04167.346910130.66169.042410137.28171.975710150.84178.8631
#Mann= 3 , 0 , 0
9849.082    0.12       09849.082    0.12       010150.84    0.12       0
#XS Ineff= 2 , 0
       0                               0
Bank Sta=9849.082,10150.84
Exp/Cntr=0.3,0.1