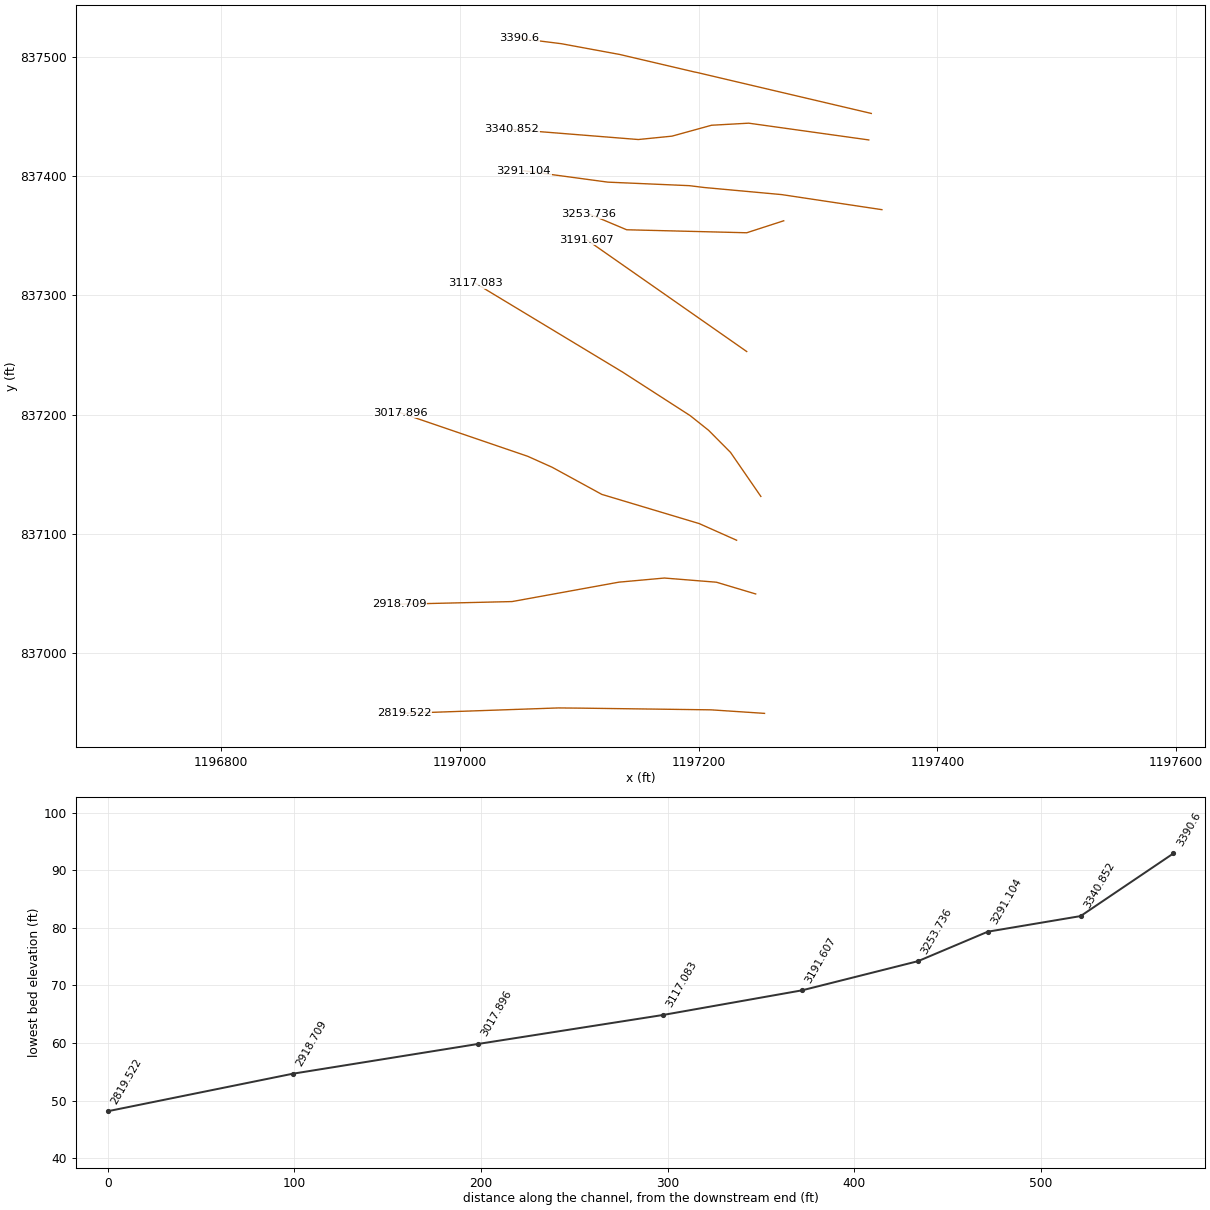
HEC-RAS study 166_ras.prj: 166

--- 166_ras.g01 (geometry) --- (continued)

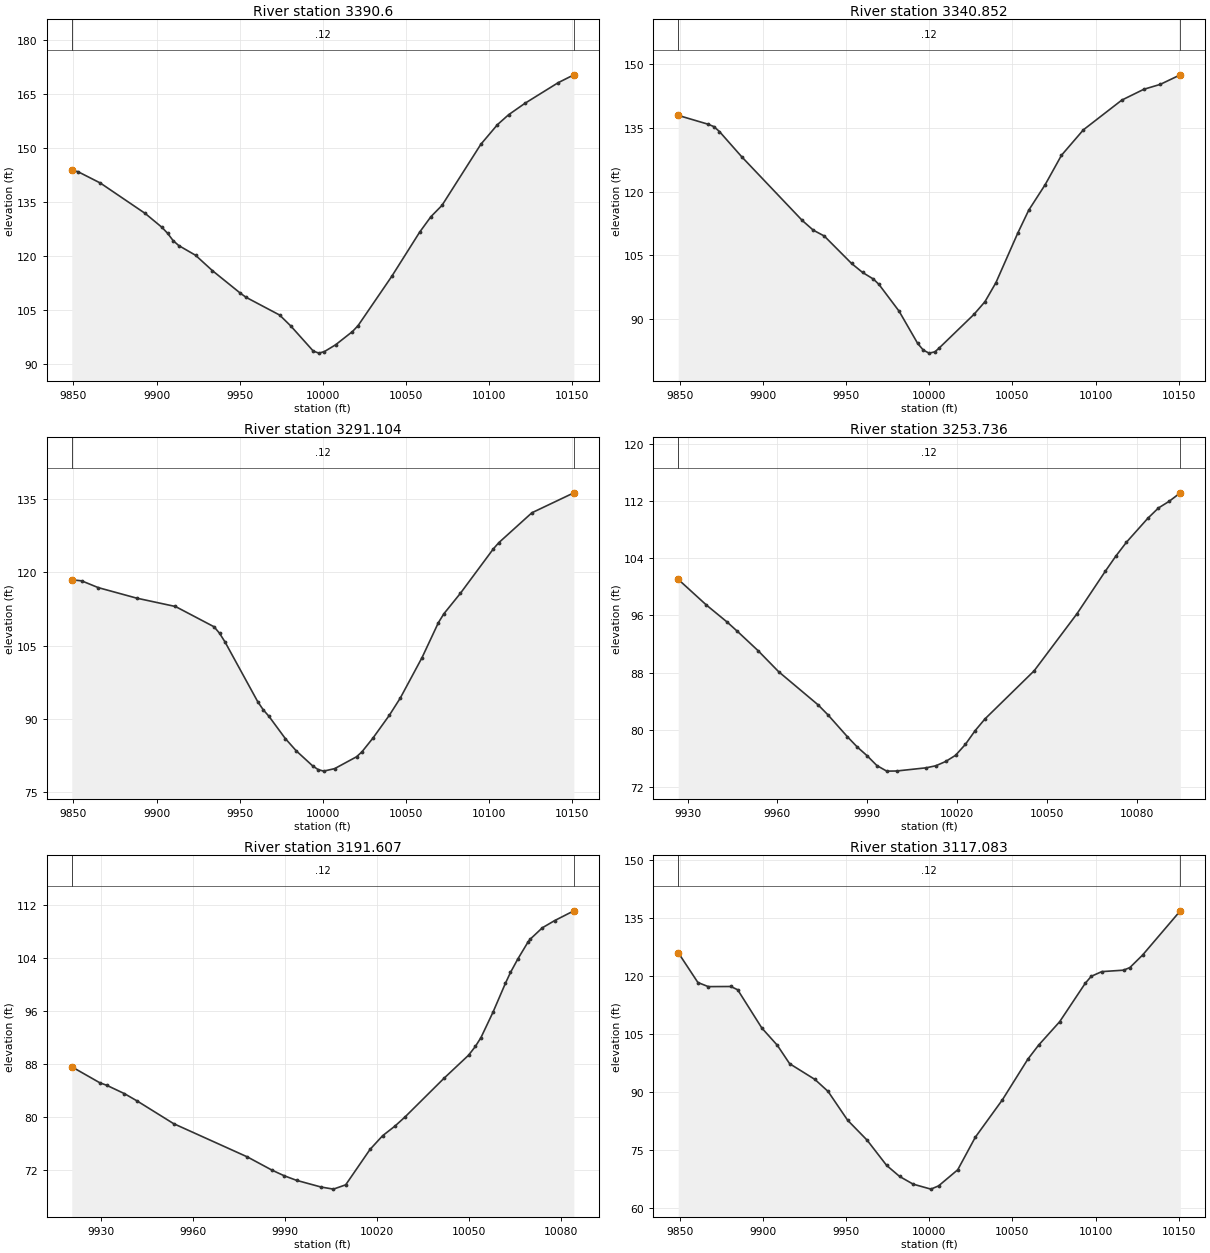
Type RM Length L Ch R = 1 ,  3390.6,49.748400,49.748400,49.748400
XS GIS Cut Line= 6
1197344.64370874837452.6965790271197198.65192934837487.083284853
1197196.68791645837487.4609796981197133.98709263 837502.18181601
1197085.12370623837511.2106821831197049.52073672837515.729077091
#Sta/Elev= 30
9849.013 143.7149852.687143.36469866.169140.20529893.134 131.7649903.246127.8924
9906.617126.25439909.987124.19839913.358122.8287 9923.47120.13199933.581115.8703
9950.352 109.6239953.805108.46519974.029103.5279 9980.77100.47939994.25293.52823
9997.62392.9512310000.9893.3862710007.7295.2768410017.8398.94502 10021.2100.5913
10041.42114.247310058.27126.574110065.01130.848810071.68133.990910095.04  150.96
10105.05156.422110111.72159.158910121.67162.371710141.51168.056910150.98 170.253
#Mann= 3 , 0 , 0
9849.013    0.12       09849.013    0.12       010150.98    0.12       0
#XS Ineff= 2 , 0
       0                               0
Bank Sta=9849.013,10150.98
Exp/Cntr=0.3,0.1

Type RM Length L Ch R = 1 ,3340.852,49.748400,49.748400,49.748400
XS GIS Cut Line= 6
1197342.52291591837430.4640645191197241.99643399837444.530612384
 1197210.8727575837442.7930790871197177.71378038837433.638867811
1197149.49536742837430.8045087831197043.64309533837439.288184711
#Sta/Elev= 30
9849.111137.88189867.229135.78899870.558135.24339873.886134.0898  9887.2128.1965
9923.671113.20589930.262110.93829936.853109.56949953.323103.10879959.895101.0106
9966.46799.440659969.75398.201059981.85791.914939993.06684.323819996.44682.76404
9999.88182.0603210003.35   82.3610005.67 83.149110026.8791.1589210033.47 94.1318
10040.0698.5959210053.21110.247710059.78115.616610069.62121.578310079.47 128.513
10092.64134.489510115.74141.471310128.95144.008110138.85145.163610150.91147.4067
#Mann= 3 , 0 , 0
9849.111    0.12       09849.111    0.12       010150.91    0.12       0
#XS Ineff= 2 , 0
       0                               0
Bank Sta=9849.111,10150.91
Exp/Cntr=0.3,0.1

Type RM Length L Ch R = 1 ,3291.104,37.367900,37.367900,37.367900
XS GIS Cut Line= 6
 1197353.5165915837371.9451954861197269.56813118837384.588922265
1197204.76187947837390.533593569 1197192.1902947837392.088937101
1197123.97343679837395.0406762041197053.60019201837404.568333306
#Sta/Elev= 30
9849.026118.4773 9854.98118.25999864.933 116.8789888.158114.71479911.383113.0138
9934.603108.86619937.898107.53769941.192105.7568 9960.9693.485969964.25491.85445
9967.54990.582679977.43386.011229984.02283.494759993.90680.412739997.201 79.6543
10000.5179.3457610007.1279.8564510020.2882.2819810023.5683.3072510030.1386.10036
10039.9890.7574910046.5594.2711810059.69 102.58210069.54109.736610072.82111.5354
 10082.7115.696610102.56124.804210105.87126.077110125.74132.183910150.96136.2608
#Mann= 3 , 0 , 0
9849.026    0.12       09849.026    0.12       010150.96    0.12       0
#XS Ineff= 2 , 0
       0                               0
Bank Sta=9849.026,10150.96
Exp/Cntr=0.3,0.1

Type RM Length L Ch R = 1 ,3253.736,62.128900,62.128900,62.128900
XS GIS Cut Line= 4
1197271.29517078837362.6084731521197240.30412057837352.557321742
1197139.79260641837355.0701095911197107.96396026837368.471644804
#Sta/Elev= 30
9926.885101.04129936.31297.44455 9943.2195.073649946.65993.768199953.55891.06627
9960.40888.132869973.53583.514369976.81782.126419983.38179.034819986.66377.60183
9989.94476.384829993.22675.003079996.50874.22748 9999.79 74.245710009.6474.68969
10012.9274.97888 10016.275.5789610019.4876.4372510022.7677.9649510026.0479.89698
10029.3381.5366210045.7488.2591910060.0196.2232410069.45102.152610073.01104.2949
10076.57106.243310083.69109.584110087.24111.0264 10090.8 111.95110094.54113.1433
#Mann= 3 , 0 , 0
9926.885    0.12       09926.885    0.12       010094.54    0.12       0
#XS Ineff= 2 , 0
       0                               0
Bank Sta=9926.885,10094.54
Exp/Cntr=0.3,0.1

Type RM Length L Ch R = 1 ,3191.607,74.524000,74.524000,74.524000
XS GIS Cut Line= 2
1197240.30412057837252.8834035251197106.28876832 837346.69415006
#Sta/Elev= 30
 9920.58  87.5869929.73985.174249931.93484.810319937.74883.541549941.75382.47646
9953.76779.021999977.79674.011829985.80672.02145 9989.8171.170049993.81570.48336
10001.8269.4728310005.8369.1588810009.8369.8068910017.7575.1343510021.8577.19953
10025.85 78.642810029.1980.0423410041.8785.8610810049.8889.3399810052.0890.65208
10053.8991.97396 10057.8 95.7865 10061.9100.192610063.52101.7948 10065.9103.8154
10069.24106.384410069.91106.795510073.91108.529610077.92109.612910084.17 111.083
#Mann= 3 , 0 , 0
 9920.58    0.12       0 9920.58    0.12       010084.17    0.12       0
#XS Ineff= 2 , 0
       0                               0
Bank Sta=9920.58,10084.17
Exp/Cntr=0.3,0.1

Type RM Length L Ch R = 1 ,3117.083,99.186900,99.186900,99.186900
XS GIS Cut Line= 6
1197252.14500452837131.2859456751197226.75951268837168.219181873
1197208.37072167837186.770836151 1197193.0345468837199.030901633
1197136.46132839 837235.564416131197013.27872261837310.086068008
#Sta/Elev= 30
9849.053126.09439860.884118.36689867.123117.30329880.674117.33439884.802116.4874
9899.324106.58559908.644102.11469916.05397.345719931.26793.267929939.17290.16543
9950.93782.706379962.66677.538429974.39671.010859982.215 68.14759990.33866.16047
   1000164.8748110005.6165.7141110017.1369.8806110027.7178.3149710043.9787.98188
10059.3198.5237310065.74102.135310078.42108.207810093.82118.165910097.43119.9729
10103.77121.184710116.83121.560510120.66122.235910128.33125.488410150.99136.9243
#Mann= 3 , 0 , 0
9849.053    0.12       09849.053    0.12       010150.99    0.12       0
#XS Ineff= 2 , 0
       0                               0
Bank Sta=9849.053,10150.99
Exp/Cntr=0.3,0.1

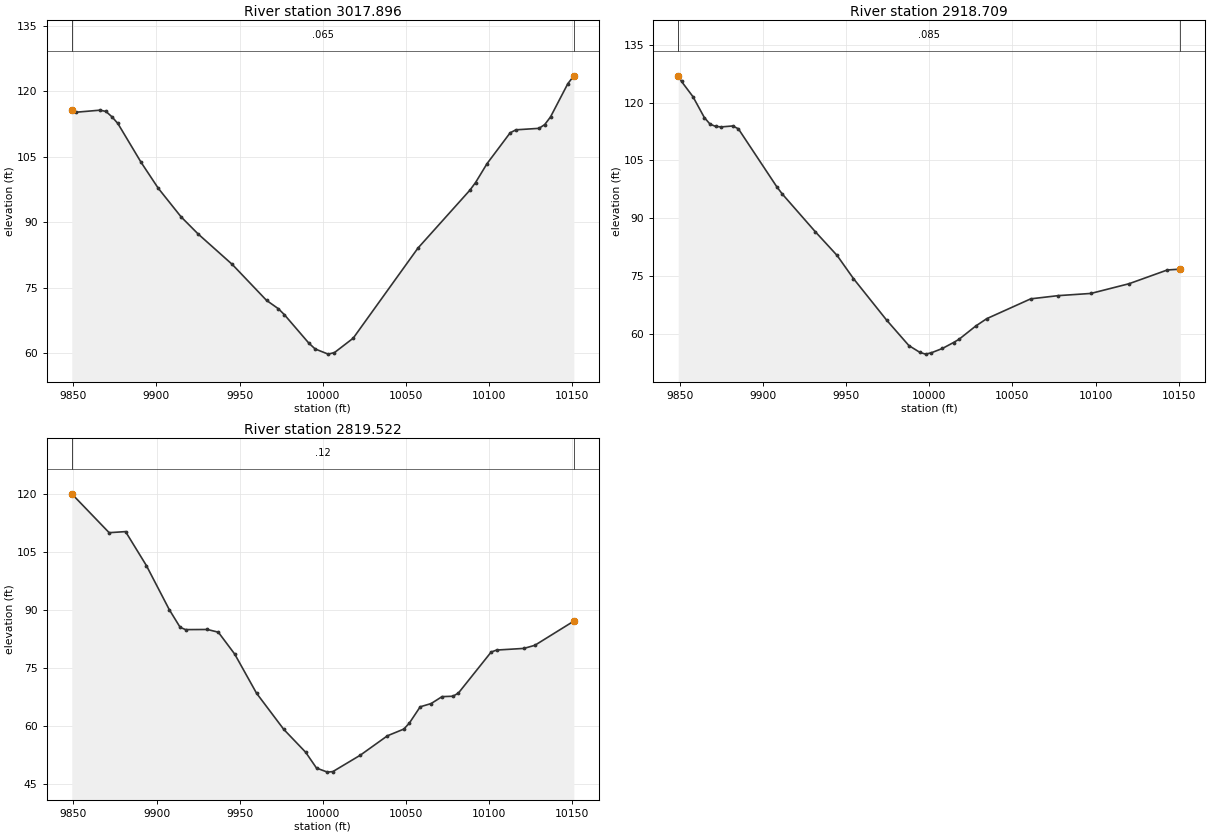
Type RM Length L Ch R = 1 ,3017.896,99.187000,99.187000,99.187000
XS GIS Cut Line= 6
1197231.85839569837094.5006541511197200.50316447837108.484400044
1197118.96076605837132.9888209881197077.39461869837155.734665544
1197056.95846067837164.9334661291196950.50891606837201.392262006
#Sta/Elev= 30
9849.093  115.659851.654115.19919866.023115.67019869.616115.38669873.208114.1708
  9876.8112.62659890.811103.70919901.08897.805369914.79191.266719925.06887.33465
9945.62380.353999966.17872.145469973.28470.234779976.90668.875619991.62862.35262
9995.456 61.013110003.2759.8350510007.0660.1933210018.3163.4865610057.1884.07686
10088.3997.3268810091.8699.10174 10098.8103.446710112.67110.487210116.14111.1735
10130.01111.511710133.48 112.38210136.95114.130710147.35121.734410150.97123.5315
#Mann= 3 , 0 , 0
9849.093   0.065       09849.093   0.065       010150.97   0.065       0
#XS Ineff= 2 , 0
       0                               0
Bank Sta=9849.093,10150.97
Exp/Cntr=0.3,0.1

Type RM Length L Ch R = 1 ,2918.709,99.186900,99.186900,99.186900
XS GIS Cut Line= 6
 1197247.8197943837049.4227806731197214.95873422837059.272648797
1197171.33929741837062.7852449221197133.22602588837059.323086495
1197043.83635186837043.033973618 1196949.3685893837040.803891678
#Sta/Elev= 30
9849.125126.99349851.104125.53149857.954121.59099864.804116.16319868.229114.4475
9871.654113.83159875.079113.72139881.929113.9654 9885.29113.21929908.425   98.13
9911.708 96.26549931.41986.535829944.59680.332849954.47974.297199974.39363.51494
9987.79356.889459994.49455.101429997.84454.6683510001.2155.0025310007.9256.13741
10014.6357.6825910017.9858.5392310027.9661.9628910034.5963.8827810061.0569.03617
10077.4869.86618 10097.270.4403910120.1672.9666310143.1376.5340310150.9776.75674
#Mann= 3 , 0 , 0
9849.125   0.085       09849.125   0.085       010150.97   0.085       0
#XS Ineff= 2 , 0
       0                               0
Bank Sta=9849.125,10150.97
Exp/Cntr=0.3,0.1

Type RM Length L Ch R = 1 ,2819.522,0.000000,0.000000,0.000000
XS GIS Cut Line= 6
1197255.22951199 836949.200060211197210.45722854836952.167528682
1197105.35241821836953.5414172661197103.35270542836953.575310761
1197082.55732448836953.7659261081196953.44384628836949.256193029
#Sta/Elev= 30
9849.016120.12949871.494110.07959881.358110.35819893.886101.58389907.633 90.2014
9914.196 85.60059917.47785.006949930.60185.042099937.16384.336819947.00778.68516
9960.13168.565679976.537 59.19669989.66153.300779996.22349.1957610002.7948.14624
10006.0748.2917610022.47 52.504610038.8957.5516210048.7359.2804910052.0260.80817
10058.5865.0432610065.1565.8819410071.7167.6695910078.2867.7776110081.5668.59789
10101.2679.2093910104.5479.7188110120.9680.1485610127.5280.9465110150.99 87.2077
#Mann= 3 , 0 , 0
9849.016    0.12       09849.016    0.12       010150.99    0.12       0
#XS Ineff= 2 , 0
       0                               0
Bank Sta=9849.016,10150.99
Exp/Cntr=0.3,0.1